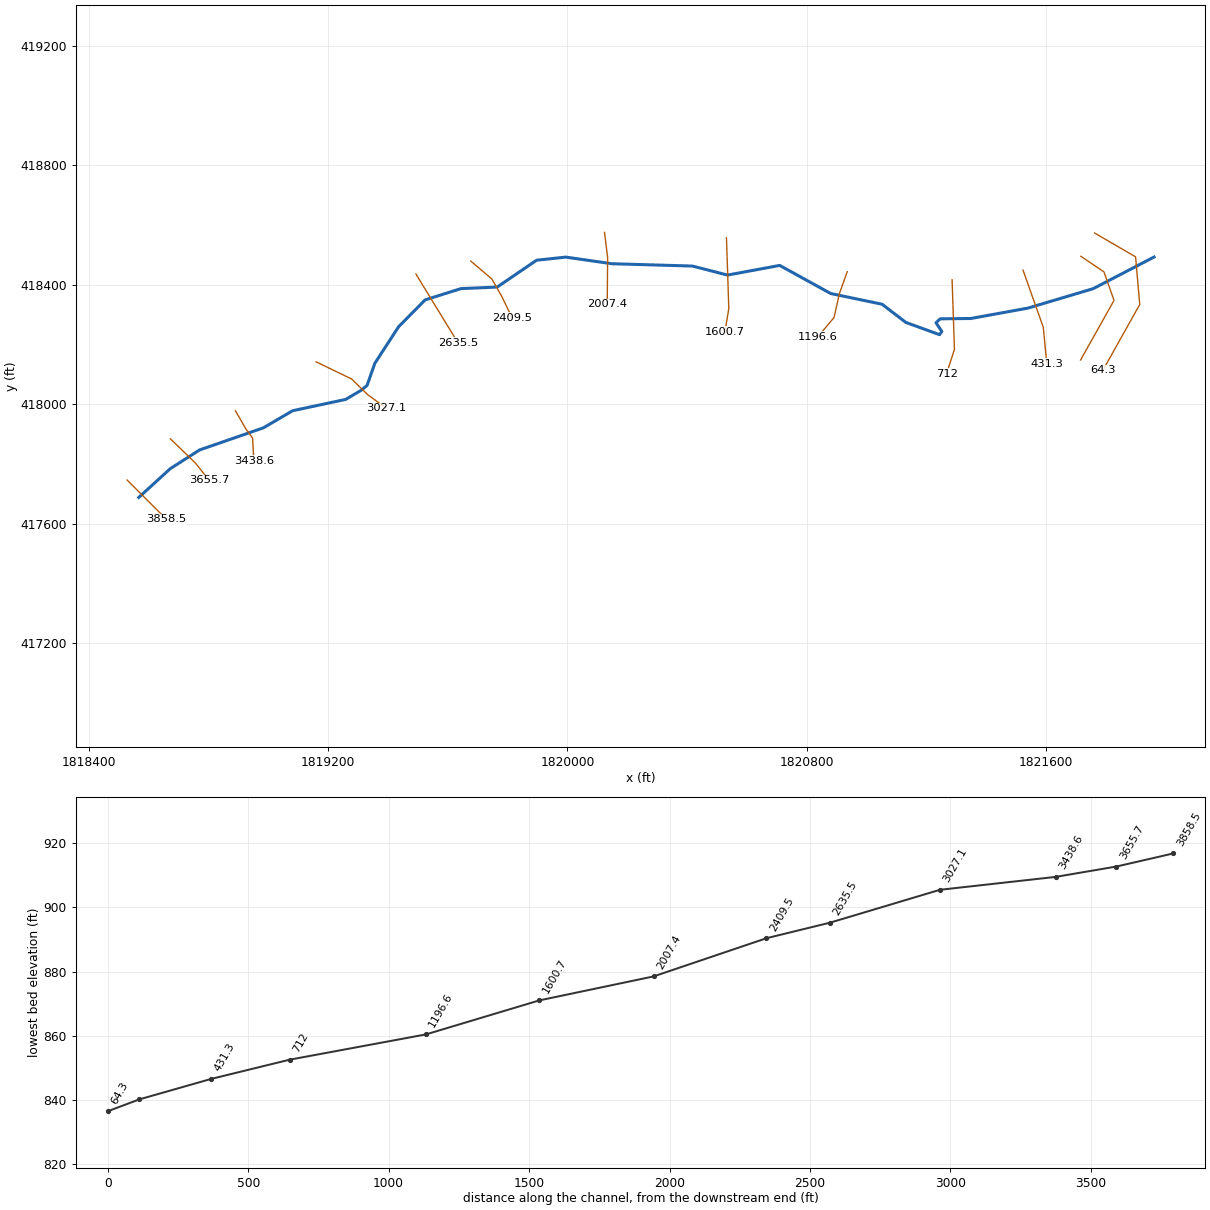
--- DOTSONFORK.prj (project) ---

Proj Title=DOTSONFORK
Current Plan=p01
Default Exp/Contr=0,0
English Units
Geom File=g01
Flow File=f01
Plan File=p01
BEGIN DESCRIPTION:
END DESCRIPTION:
DSS Export Rating Curves= 0
DSS Export Rating Curve Sorted= 0
DSS Export Volume Flow Curves= 0
DXF OffsetX= 0
DXF OffsetY= 0
DXF ScaleX= 0
DXF ScaleY= 0

--- DOTSONFORK.p01 (plan) ---

Plan Title=Floodplain
Program Version=4.00
Geom File=g01
Flow File=f01
K Sum by GR=0
Std Step Tol=0.01
Critical Tol=0.01
Num of Std Step Trials=20
Max Error Tol=0.3
Flow Tol Ratio=0.001
Split Flow NTrial=30
Split Flow Tol=0.02
Split Flow Ratio=0.02
Log Output Level=0
Friction Slope Method=1
Unsteady Friction Slope Method=2
Unsteady Bridges Friction Slope Method=1
Global Log Level=0
CheckData=False
Run HTab=0
Run UNet=0
Run PostProcess=0
UNET Theta=0
UNET Theta Warmup=0
UNET ZTol=0
UNET ZSATol=0
UNET MxIter=0
UNET MaxInSteps=0
UNET DtIC=0
UNET DtMin=0
UNET MaxCRTS=0
UNET WFStab=0
UNET SFStab=0
UNET WFX=0
UNET SFX=0
UNET DSS MLevel=0
UNET DZMax Abort=0
UNET Convert EG Bridges=0
UNET Use Existing IB Tables=0
UNET Froude Limit=0
UNET Froude Power=0
Write IC File=0
Echo Input=False
Echo Output=False
Write Detailed=0

--- DOTSONFORK.f01 (steady flow) ---

Flow Title=NFF Regression Equation
Program Version=4.10
Number of Profiles= 1
Profile Names=P100yr
River Rch & RM=DOTSONFORK,Main            ,3858.5
895.3831
River Rch & RM=DOTSONFORK,Main            ,712
 992.824
Boundary for River Rch & Prof#=DOTSONFORK,Main            , 1
Up Type= 0
Dn Type= 3
Dn Slope=0.025
DSS Import GetInterval= 0
DSS Import GetPeak= 0
DSS Import FillOption= 0

--- DOTSONFORK.g01 (geometry) ---

Geom Title=USGS 10m DEM
Program Version=4.10

River Reach=DOTSONFORK      ,Main
Reach XY= 30
     1818567.408      417688.105     1818672.732      417784.524
     1818770.388      417847.024      1818983.93      417921.243
     1819081.586      417978.534     1819258.669      418016.295
     1819309.451      418046.243     1819330.284       418063.17
     1819356.326      418137.388     1819435.753      418259.784
     1819524.294      418349.628     1819644.086      418387.388
      1819765.18      418392.597      1819896.69       418482.44
     1819994.347      418492.857     1820147.992      418470.722
     1820417.524      418462.909     1820534.711      418432.744
     1820709.044       418465.04     1820879.763      418370.895
     1821051.204      418335.088     1821130.414      418274.324
     1821243.261      418233.092     1821250.857      418243.942
     1821231.326      418273.239     1821245.432       418286.26
     1821347.428      418287.345       1821538.4      418322.067
     1821756.499      418387.171     1821960.002      418493.143

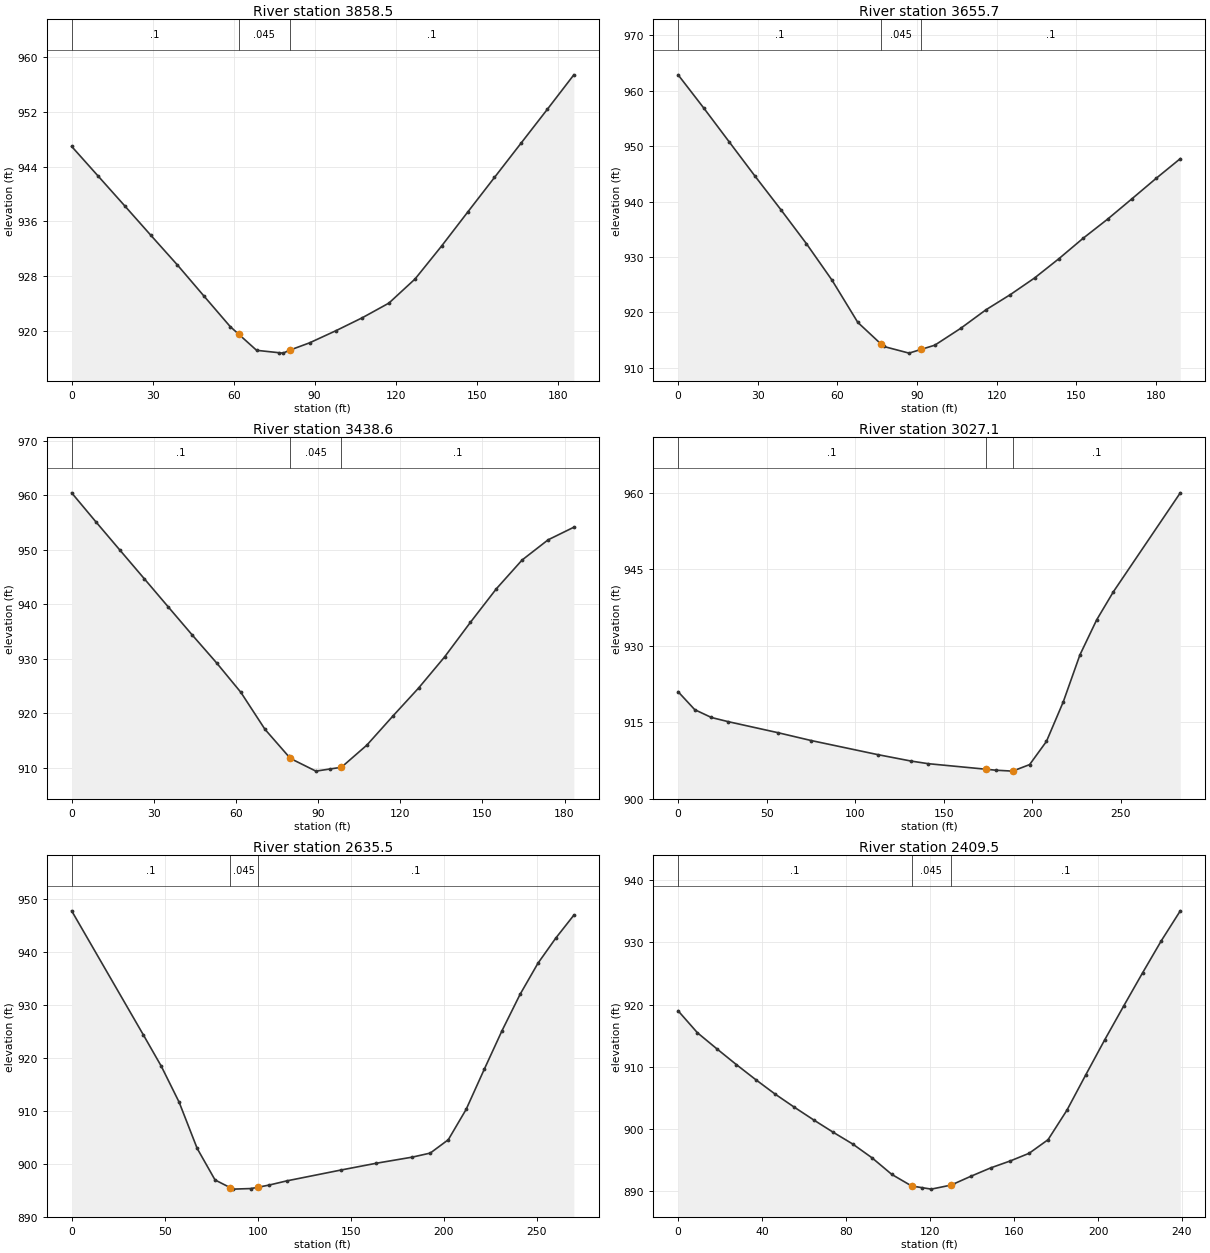
Type RM Length L Ch R = 1 ,3858.5  ,202.2,202.8,203.2
XS GIS Cut Line= 2
     1818528.635      417746.329     1818660.145      417614.819
#Sta/Elev= 23
       0  946.96     9.8  942.63    19.6   938.3    29.4  933.94    39.2  929.62
    48.9  925.14    58.7  920.64    61.8  919.54    68.5  917.16    76.8  916.81
    78.3  916.75   80.96  917.21    88.1  918.25    97.9  920.03   107.7  921.93
   117.5  924.06   127.2  927.59     137  932.39   146.8  937.42   156.6  942.42
   166.4  947.41   176.2  952.39     186  957.42
#Mann= 3 , 0 , 0
       0      .1       0    61.8    .045       0   80.96      .1       0
Bank Sta=61.8,80.96
XS Rating Curve= 0 ,0
Exp/Cntr=0.3,0.1

Type RM Length L Ch R = 1 ,3655.7  ,221.4,217,212
XS GIS Cut Line= 3
     1818673.166       417884.35     1818756.499      417803.621
     1818802.072      417746.329
#Sta/Elev= 23
       0  962.84     9.7  956.83    19.3  950.72      29  944.56    38.7  938.54
    48.3  932.43      58  925.81    67.7  918.21    76.6  914.24    77.4  913.88
      87  912.67    91.6  913.35    96.7   914.1   106.4  917.12     116  920.49
   125.2  923.23   134.3  926.22   143.5  929.71   152.6  933.38   161.8  936.82
   170.9  940.46   180.1  944.18   189.2  947.73
#Mann= 3 , 0 , 0
       0      .1       0    76.6    .045       0    91.6      .1       0
Bank Sta=76.6,91.6
XS Rating Curve= 0 ,0
Exp/Cntr=0.3,0.1

Type RM Length L Ch R = 1 ,3438.6  ,407.2,411.5,416.2
XS GIS Cut Line= 4
     1818890.614        417978.1      1818925.77      417916.902
     1818947.906      417886.954     1818951.812      417811.434
#Sta/Elev= 23
       0  960.42     8.8  955.14    17.6  949.94    26.5   944.7    35.3  939.51
    44.1  934.34    52.9  929.29    61.8  923.87    70.6   917.1    79.2  912.16
    79.9  911.76    89.2  909.44    94.2  909.82    98.5  910.14   107.8   914.2
   117.3  919.52   126.7  924.66   136.2  930.36   145.6  936.68   155.1  942.84
   164.5  948.11     174  951.81   183.4  954.12
#Mann= 3 , 0 , 0
       0      .1       0    79.9    .045       0    98.5      .1       0
Bank Sta=79.9,98.5
XS Rating Curve= 0 ,0
Exp/Cntr=0.3,0.1

Type RM Length L Ch R = 1 ,3027.1  ,396.8,391.6,386.1
XS GIS Cut Line= 4
     1819160.145      418142.163     1819278.635      418084.871
     1819333.322      418031.486      1819394.52      417987.215
#Sta/Elev= 19
       0  920.99     9.4  917.47    18.8  915.94    28.2  915.13    56.4  912.96
    75.2  911.42   112.8  908.66   131.6   907.4   141.2  906.89   173.9   905.8
   179.4  905.61   188.9  905.43   198.5  906.71     208  911.25   217.5     919
   226.9   928.2   236.4  935.09   245.8  940.57   283.6  959.96
#Mann= 3 , 0 , 0
       0      .1       0   173.9    .045       0   188.9      .1       0
Bank Sta=173.9,188.9
XS Rating Curve= 0 ,0
Exp/Cntr=0.3,0.1

Type RM Length L Ch R = 1 ,2635.5  ,226.2,226,225.6
XS GIS Cut Line= 2
     1819493.479      418436.434     1819634.104      418205.965
#Sta/Elev= 24
       0   947.7    38.6  924.27    48.2  918.38    57.8  911.59    67.5  902.87
    77.1  896.93    85.2  895.49    86.8   895.2    96.4  895.31   100.2  895.56
   106.1  895.96   115.7  896.76   144.6  898.79   163.9  900.09   183.2  901.24
   192.8     902   202.5  904.52   212.1  910.25   221.8  917.78   231.4   925.1
   241.1  931.95   250.7  937.81   260.3  942.56     270  946.88
#Mann= 3 , 0 , 0
       0      .1       0    85.2    .045       0   100.2      .1       0
Bank Sta=85.2,100.2
XS Rating Curve= 0 ,0
Exp/Cntr=0.3,0.1

Type RM Length L Ch R = 1 ,2409.5  ,413.4,402.1,389.7
XS GIS Cut Line= 4
     1819677.072      418479.402     1819747.385      418419.506
     1819779.937      418362.215     1819815.093      418289.298
#Sta/Elev= 29
       0  919.02     9.2  915.49    18.5   912.9    27.7  910.39      37  907.95
    46.2  905.64    55.4  903.52    64.7  901.46    73.9   899.5    83.1  897.63
    92.4  895.39   101.8  892.73   111.2  890.88   116.1  890.61   120.6  890.37
     130  891.02   131.1  891.18   139.4  892.43   148.8  893.77   158.3  894.91
   167.2  896.13   176.2  898.31   185.2  903.05   194.2  908.75   203.2  914.36
   212.2  919.77   221.2   925.1   230.2   930.3   239.2  935.08
#Mann= 3 , 0 , 0
       0      .1       0   111.2    .045       0     130      .1       0
Bank Sta=111.2,130
XS Rating Curve= 0 ,0
Exp/Cntr=0.3,0.1

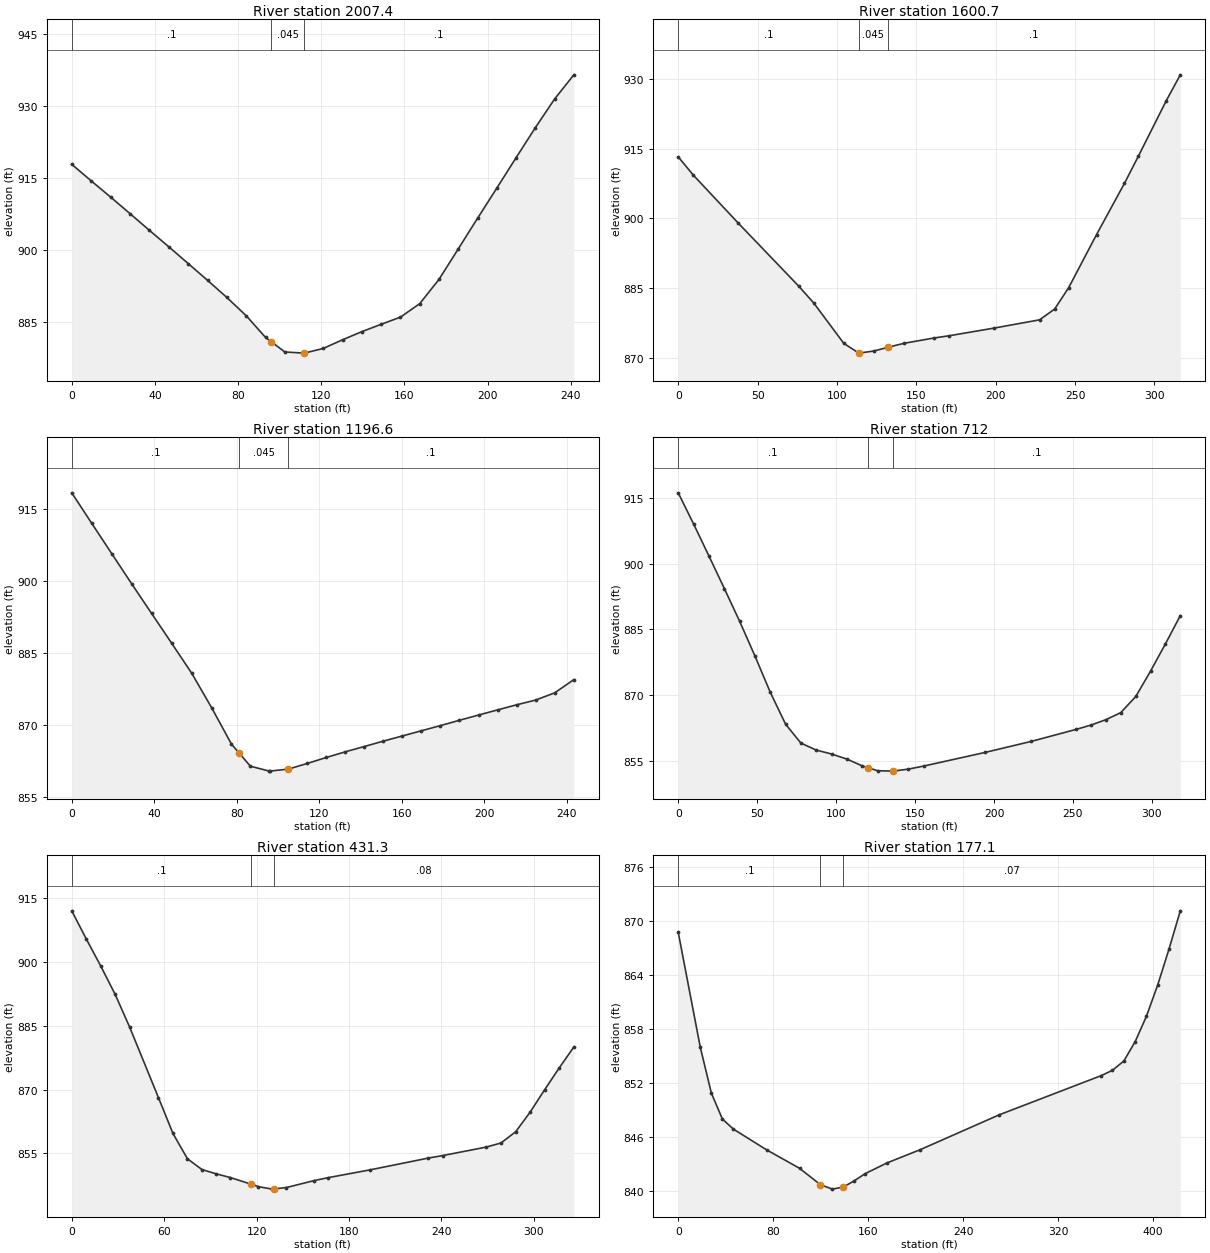
Type RM Length L Ch R = 1 ,2007.4  ,405.9,406.8,407.7
XS GIS Cut Line= 3
     1820123.687      418575.756     1820134.104      418492.423
     1820132.801      418334.871
#Sta/Elev= 29
       0  917.79     9.3  914.36    18.7  910.96      28  907.53    37.3  904.06
    46.7  900.61      56  897.13    65.3  893.64    74.6  890.07      84  886.22
    93.2  881.75      96  880.84   102.5  878.72     111   878.5   111.8  878.48
     121  879.46   130.3  881.27   139.6  882.96   148.9   884.5   158.1  885.97
   167.4  888.79   176.7  893.87   185.9  900.17   195.2  906.57   204.5  912.87
   213.7  919.15     223  925.43   232.3  931.42   241.5  936.42
#Mann= 3 , 0 , 0
       0      .1       0      96    .045       0   111.8      .1       0
Bank Sta=96,111.8
XS Rating Curve= 0 ,0
Exp/Cntr=0.3,0.1

Type RM Length L Ch R = 1 ,1600.7  ,410.9,404.1,398.1
XS GIS Cut Line= 3
     1820531.239      418557.527     1820539.051      418320.548
     1820526.031      418242.423
#Sta/Elev= 21
       0  913.24     9.5  909.31    37.9  898.96    75.9  885.43    85.4  881.79
   104.3  873.12   113.8  871.02   123.3  871.48   132.1  872.27   142.3  873.14
   161.2  874.28   170.7  874.76   199.2  876.42   227.6  878.18   237.1  880.49
   245.9  885.06   263.5   896.5   281.1  907.54   289.9   913.4   307.5  925.36
   316.3  930.89
#Mann= 3 , 0 , 0
       0      .1       0   113.8    .045       0   132.1      .1       0
Bank Sta=113.8,132.1
XS Rating Curve= 0 ,0
Exp/Cntr=0.3,0.1

Type RM Length L Ch R = 1 ,1196.6  ,445.7,484.6,492
XS GIS Cut Line= 4
     1820934.885      418444.246     1820908.843      418371.329
     1820890.614        418290.6     1820837.229      418226.798
#Sta/Elev= 29
       0  918.35     9.7  911.99    19.4  905.68      29  899.44    38.7  893.25
    48.4  887.07    58.1  880.84    67.8  873.63    77.4  866.07    81.3  864.11
    86.6  861.45    95.8  860.43    96.3  860.45     105  860.85   114.2  862.03
   123.4  863.27   132.6  864.45   141.8  865.55     151  866.67   160.2  867.74
   169.4  868.82   178.7   869.9   187.9  871.01   197.2   872.1   206.4  873.17
   215.6  874.23   224.9  875.22   234.1  876.72   243.4  879.47
#Mann= 3 , 0 , 0
       0      .1       0    81.3    .045       0     105      .1       0
Bank Sta=81.3,105
XS Rating Curve= 0 ,0
Exp/Cntr=0.3,0.1

Type RM Length L Ch R = 1 ,712     ,273.5,280.6,287.4
XS GIS Cut Line= 3
     1821285.145      418416.902     1821292.958      418183.829
     1821266.916        418103.1
#Sta/Elev= 28
       0  916.22     9.7  909.12    19.4  901.81    29.2  894.34    38.9  886.84
    48.6  878.89    58.3  870.61      68  863.31    77.7  858.99    87.4  857.39
    97.2  856.49   106.9  855.32   116.6  853.77     120  853.38   126.3  852.67
     136  852.58   145.8  853.04   155.5  853.74   194.3  856.85   223.5  859.37
     252  862.12   261.5  863.12   270.9  864.35   280.3  865.96   289.8  869.65
   299.2  875.48   308.6   881.7     318  888.14
#Mann= 3 , 0 , 0
       0      .1       0     120    .045       0     136      .1       0
Bank Sta=120,136
XS Rating Curve= 0 ,0
Exp/Cntr=0.3,0.1

Type RM Length L Ch R = 1 ,431.3   ,254.4,254.3,254.3
XS GIS Cut Line= 4
     1821522.124      418449.454     1821553.374      418360.913
     1821589.833      418258.048     1821601.551      418135.652
#Sta/Elev= 28
       0  912.06     9.4  905.45    18.8  899.08    28.2  892.38    37.6  884.68
    56.3  868.09    65.7  859.67    75.1  853.72    84.5  851.18    93.9  850.16
     103  849.29   116.3  847.75   121.2  847.15   130.3  846.57   131.3  846.61
   139.4  846.95   157.6   848.6   166.6  849.28   193.9  851.12   231.4  853.87
   240.9  854.47   269.2  856.47   278.7  857.43   288.2  860.06   297.6  864.68
   307.1  869.99   316.5  875.09     326  880.02
#Mann= 3 , 0 , 0
       0      .1       0   116.3    .045       0   131.3     .08       0
Bank Sta=116.3,131.3
XS Rating Curve= 0 ,0
Exp/Cntr=0.3,0.1

Type RM Length L Ch R = 1 ,177.1   ,118.4,112.8,106.4
XS GIS Cut Line= 4
     1821715.518      418495.548     1821792.558      418443.465
     1821826.196      418347.979     1821714.433      418148.326
#Sta/Elev= 23
       0   868.7    18.6  855.95    27.9  850.89    37.2  848.01    46.5  846.89
    74.4   844.6   102.2  842.55   119.7  840.74   129.8  840.24     139  840.47
   148.2  841.15   157.4  841.95   175.8  843.14   203.8  844.61   270.5  848.48
   356.3  852.82   365.8  853.41   375.4  854.44   384.9  856.57   394.4  859.38
     404  862.89   413.5  866.86     423  871.09
#Mann= 3 , 0 , 0
       0      .1       0   119.7    .045       0     139     .07       0
Bank Sta=119.7,139
XS Rating Curve= 0 ,0
Exp/Cntr=0.3,0.1

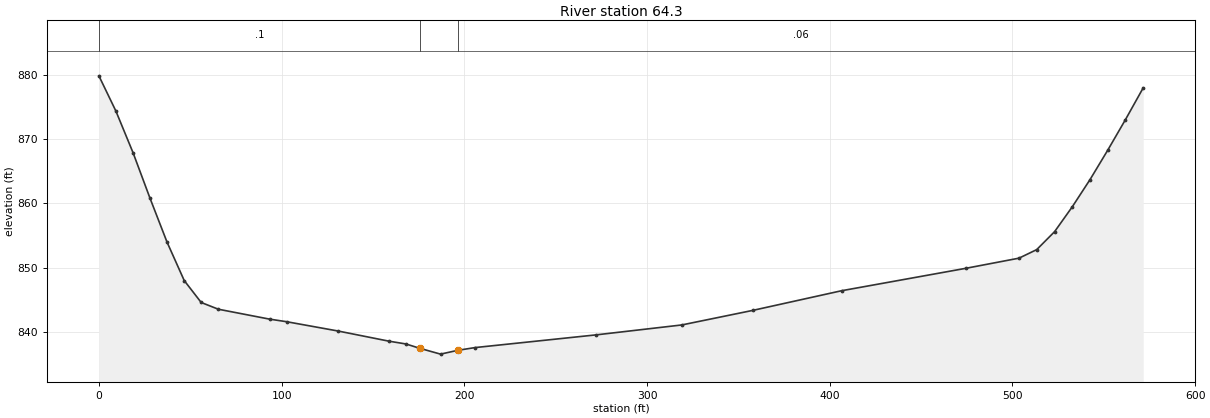
Type RM Length L Ch R = 1 ,64.3    ,59,64.3,70
XS GIS Cut Line= 4
     1821761.057      418573.673     1821898.209      418493.812
     1821912.098       418334.09     1821788.834      418113.604
#Sta/Elev= 30
       0  879.87     9.3  874.39    18.7   867.9      28   860.8    37.3  853.98
    46.7     848      56  844.58    65.4  843.53    93.4  841.99   102.7  841.59
   130.7  840.15   158.7  838.56   168.1  838.12   175.7  837.44     187  836.54
   196.4  837.13   205.9  837.56   271.9  839.53     319  841.08   357.9  843.35
   406.5  846.41   474.5   849.9   503.6  851.48   513.3  852.81   523.1  855.61
   532.8  859.49   542.5  863.72   552.2   868.3   561.9  873.06   571.6     878
#Mann= 3 , 0 , 0
       0      .1       0   175.7    .045       0   196.4     .06       0
Bank Sta=175.7,196.4
XS Rating Curve= 0 ,0
Exp/Cntr=0.3,0.1

Chan Stop Cuts=-1
Use User Specified Reach Order=0
Composite Channel Slope=5